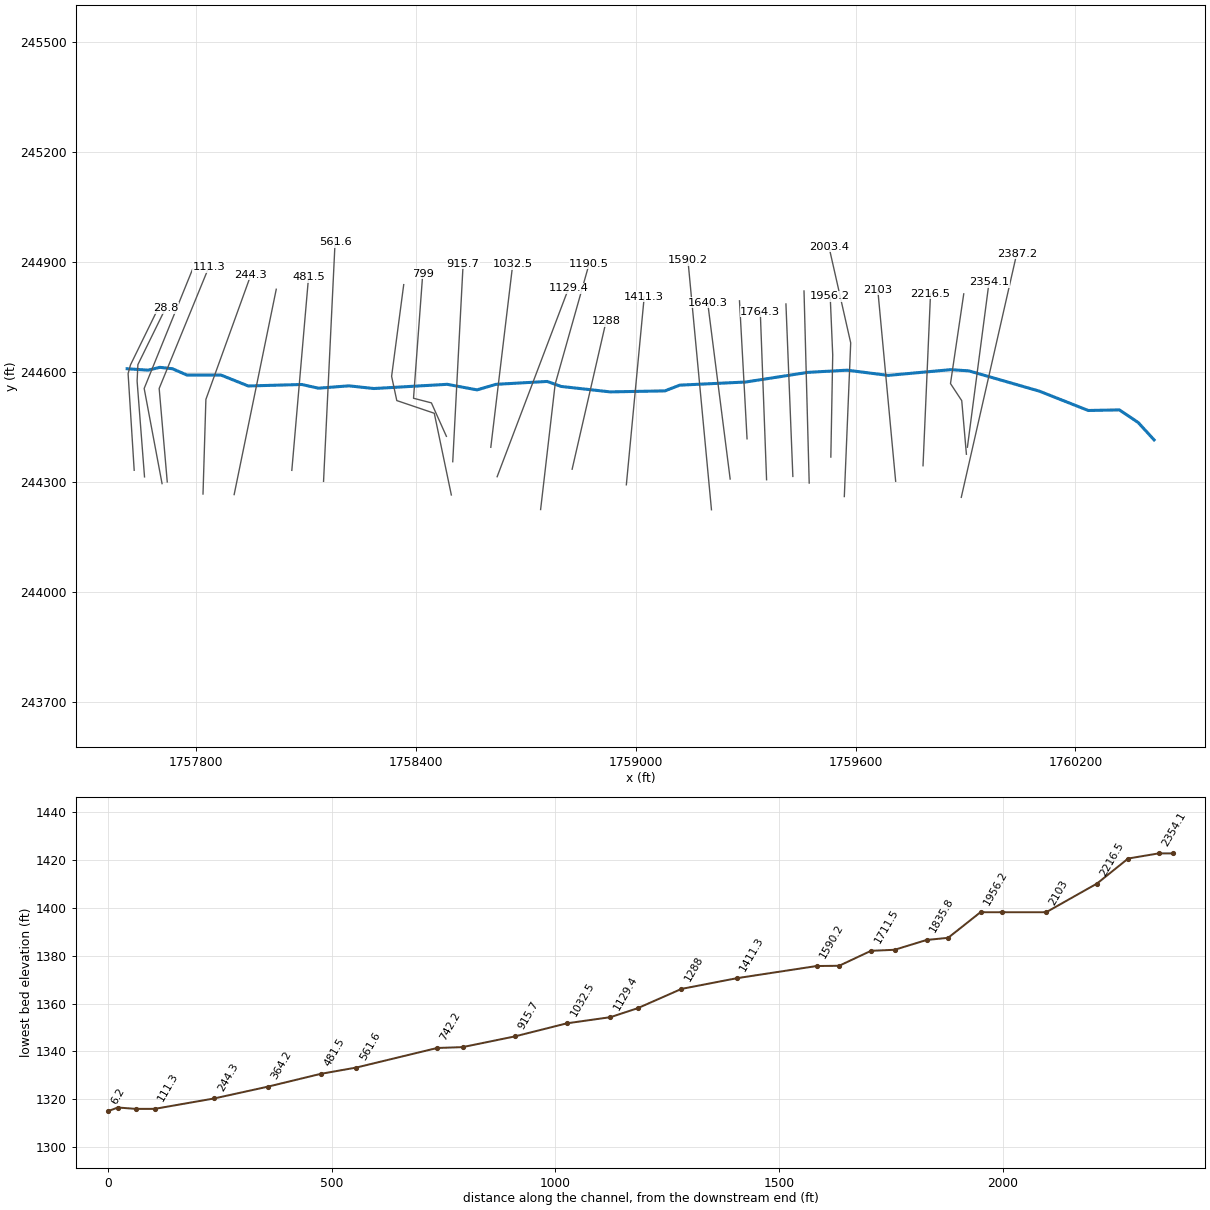
--- McDnldFk.prj (project) ---

Proj Title=McDnldFk
Current Plan=p01
Default Exp/Contr=0,0
English Units
Geom File=g01
Flow File=f01
Plan File=p01
BEGIN DESCRIPTION:
END DESCRIPTION:
DSS Export Rating Curves= 0
DSS Export Rating Curve Sorted= 0
DSS Export Volume Flow Curves= 0
DXF OffsetX= 0
DXF OffsetY= 0
DXF ScaleX= 0
DXF ScaleY= 0

--- McDnldFk.p01 (plan) ---

Plan Title=Floodplain
Program Version=4.00
Geom File=g01
Flow File=f01
K Sum by GR=0
Std Step Tol=0.01
Critical Tol=0.01
Num of Std Step Trials=20
Max Error Tol=0.3
Flow Tol Ratio=0.001
Split Flow NTrial=30
Split Flow Tol=0.02
Split Flow Ratio=0.02
Log Output Level=0
Friction Slope Method=1
Unsteady Friction Slope Method=2
Unsteady Bridges Friction Slope Method=1
Global Log Level=0
CheckData=False
Run HTab=0
Run UNet=0
Run PostProcess=0
UNET Theta=0
UNET Theta Warmup=0
UNET ZTol=0
UNET ZSATol=0
UNET MxIter=0
UNET MaxInSteps=0
UNET DtIC=0
UNET DtMin=0
UNET MaxCRTS=0
UNET WFStab=0
UNET SFStab=0
UNET WFX=0
UNET SFX=0
UNET DSS MLevel=0
UNET DZMax Abort=0
UNET Convert EG Bridges=0
UNET Use Existing IB Tables=0
UNET Froude Limit=0
UNET Froude Power=0
Write IC File=0
Echo Input=False
Echo Output=False
Write Detailed=0

--- McDnldFk.f01 (steady flow) ---

Flow Title=NFF Regression Equation
Program Version=4.00
Number of Profiles=1
Profile Names=P100yr
River Rch & RM=McDnldFk,Main      ,2387.2
545.2195
River Rch & RM=McDnldFk,Main      ,2003.4
583.8930
River Rch & RM=McDnldFk,Main      ,1190.5
598.9949
River Rch & RM=McDnldFk,Main      ,244.3
653.4285
Boundary for River Rch & Prof#=McDnldFk,Main      ,1
Up Type=0
Dn Type=3
Dn Slope=0.017232

--- McDnldFk.g01 (geometry) ---

Geom Title=USGS 10m DEM
Program Version=4.00

River Reach=McDnldFk        ,Main
Reach XY= 30
     1760414.564      244415.222     1760371.248      244462.549
      1760319.91      244497.041     1760234.882      244495.437
     1760100.923      244548.379      1759908.72      244603.639
     1759859.541      244606.856     1759688.563      244591.229
     1759576.416      244605.477     1759469.325      244599.502
     1759299.846      244573.175     1759119.556      244564.571
      1759079.11      244548.944     1758929.734      244546.186
     1758796.175      244561.005     1758757.837      244574.683
     1758618.114       244566.87     1758566.177      244551.702
     1758484.824       244566.87     1758284.431      244555.379
     1758216.408      244562.733     1758133.217      244556.298
     1758087.715       244566.41     1757941.576      244562.358
     1757867.098      244592.148     1757774.256      244592.148
     1757734.623      244609.414     1757700.305      244613.188
     1757668.084      244605.477     1757610.968      244609.435

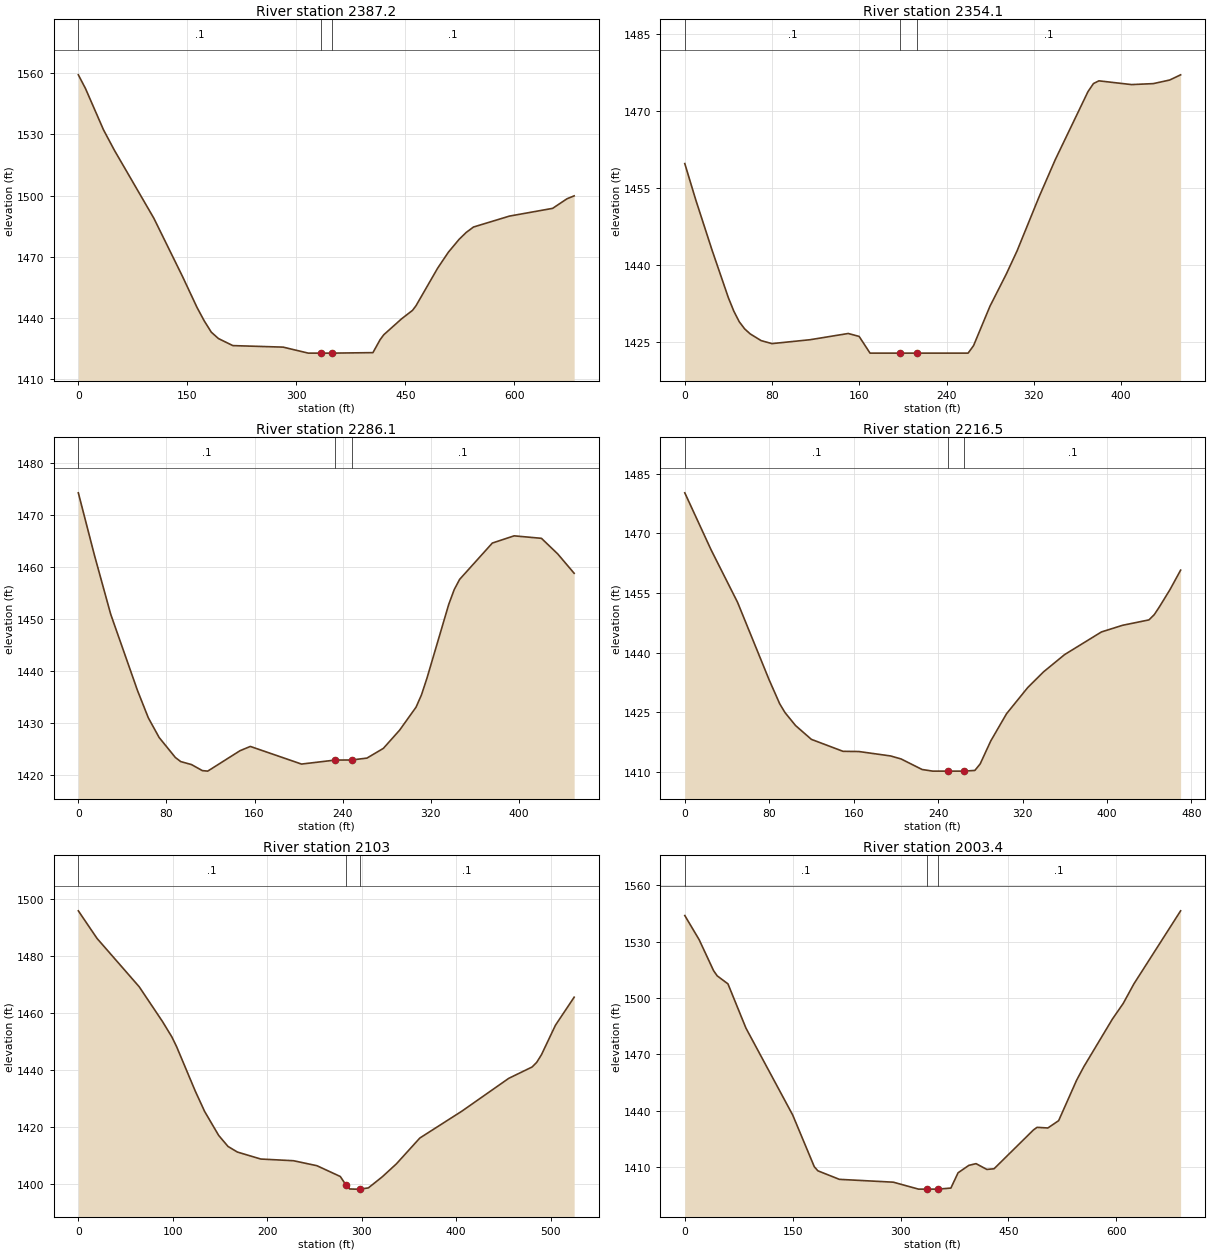
Type RM Length L Ch R = 1 ,2387.2  ,31,33.2,35.3
XS GIS Cut Line= 3
     1759888.211      244258.328     1759963.951      244591.067
      1760039.69      244923.806
#Sta/Elev= 30
       0 1559.23     9.9 1552.48    34.6 1532.31    49.5 1522.35   103.9 1488.98
   143.4 1460.41   163.2 1445.36   173.1 1438.77     183 1433.12   192.9 1429.97
   212.7 1426.53   281.9 1425.78   316.5 1422.84   333.8 1422.84   348.8 1422.84
   405.5 1423.08   415.4 1429.43   420.4 1431.83   445.1  1439.7     460 1443.79
   464.9 1446.12   494.6 1464.48   509.4 1472.32   524.2 1478.63   534.1 1482.05
     544 1484.65   593.5    1490   652.8 1493.78   672.6 1498.48   682.5 1499.91
#Mann= 3 , 0 , 0
       0      .1       0   333.8    .045       0   348.8      .1       0
Bank Sta=333.8,348.8
XS Rating Curve= 0 ,0
Exp/Cntr=0.3,0.1

Type RM Length L Ch R = 1 ,2354.1  ,68.3,68,67.6
XS GIS Cut Line= 2
     1759904.977      244395.202     1759964.052      244845.823
#Sta/Elev= 30
       0 1459.71      10 1452.69      25 1442.87      40 1433.59      45 1430.98
    49.9 1428.95    54.9 1427.55    59.9 1426.59    69.9 1425.28    79.9 1424.69
   114.9 1425.45   149.8 1426.66   159.8 1426.09   169.8 1422.84   197.5 1422.84
   212.5 1422.84   259.7 1422.84   264.7  1424.3   279.7 1431.95   294.7 1438.22
   304.6 1442.74   324.6 1453.17   339.6 1460.48   369.6 1473.72   374.6 1475.28
   379.6 1475.81   409.5 1475.08   429.5 1475.27   444.5 1475.97   454.5 1476.98
#Mann= 3 , 0 , 0
       0      .1       0   197.5    .045       0   212.5      .1       0
#XS Ineff= 2 , 0
          151.46 1426.49
Permanent Ineff=
       F       F
Bank Sta=197.5,212.5
XS Rating Curve= 0 ,0
Exp/Cntr=0.3,0.1

Type RM Length L Ch R = 1 ,2286.1  ,67.3,69.6,71.9
XS GIS Cut Line= 4
     1759902.229      244375.968     1759889.495      244522.257
     1759858.763      244568.922     1759894.972      244813.808
#Sta/Elev= 30
       0 1474.34    14.7 1462.26    29.4 1450.94    53.8  1436.2    63.6 1430.96
    73.4 1427.18    88.1 1423.33      93 1422.54   102.8 1421.96   112.6  1420.8
   117.5  1420.7   146.8 1424.63   156.2 1425.46   202.7 1422.06   233.2 1422.83
   248.2 1422.85   262.1 1423.21     277 1425.08   291.8  1428.6   306.7 1433.02
   311.6 1435.38   316.6  1438.6   336.4 1452.84   341.4  1455.7   346.3 1457.66
     376 1464.66   395.8 1466.05   420.6 1465.57   435.4 1462.56   450.3 1458.83
#Mann= 3 , 0 , 0
       0      .1       0   233.2    .045       0   248.2      .1       0
#XS Ineff= 2 , 0
          156.78  1425.3
Permanent Ineff=
       F       F
Bank Sta=233.2,248.2
XS Rating Curve= 0 ,0
Exp/Cntr=0.3,0.1

Type RM Length L Ch R = 1 ,2216.5  ,110.4,113.5,116.7
XS GIS Cut Line= 2
     1759783.778      244344.582     1759804.248      244813.808
#Sta/Elev= 30
       0 1480.23      25 1465.84      50 1452.68    79.9 1433.19    89.9 1427.17
    94.9 1424.97   104.9  1421.7   119.9 1418.22   149.9 1415.21   164.9 1415.16
   194.9 1414.05   204.9 1413.29   224.8 1410.64   234.8 1410.23   249.7 1410.23
   264.7 1410.23   274.8 1410.41   279.8 1412.04   289.8  1417.8   304.8 1424.67
   324.8 1431.23   339.8 1435.19   359.8 1439.54   394.7 1445.24   414.7 1446.91
   439.7 1448.27   444.7 1449.58   449.7 1451.59   459.7 1455.92   469.7 1460.78
#Mann= 3 , 0 , 0
       0      .1       0   249.7    .045       0   264.7      .1       0
Bank Sta=249.7,264.7
XS Rating Curve= 0 ,0
Exp/Cntr=0.3,0.1

Type RM Length L Ch R = 1 ,2103    ,102.7,99.6,96.6
XS GIS Cut Line= 2
     1759709.077      244302.269     1759660.265      244825.031
#Sta/Elev= 30
       0 1495.73    19.8 1486.07    64.4 1469.15    89.2 1456.91    99.1 1451.52
     104 1448.19   123.8  1432.6   133.7 1425.47   148.6 1417.06   158.5 1413.19
   168.4 1411.23   193.2 1408.78   227.8 1408.19   252.6 1406.45   277.4 1402.66
   283.4 1399.68   287.3  1398.3   292.2 1398.24   298.4 1398.24   307.1 1398.67
     322  1402.6   336.8  1407.1   361.6 1416.14   406.2 1425.57   455.7 1437.04
   480.5 1441.03   485.4 1442.67   490.4 1445.34   505.2 1455.66     525 1465.47
#Mann= 3 , 0 , 0
       0      .1       0   283.4    .045       0   298.4      .1       0
Bank Sta=283.4,298.4
XS Rating Curve= 0 ,0
Exp/Cntr=0.3,0.1

Type RM Length L Ch R = 1 ,2003.4  ,46.6,47.2,47.7
XS GIS Cut Line= 3
     1759568.904      244260.455     1759586.353      244679.969
     1759526.853      244942.759
#Sta/Elev= 30
       0 1543.98      20 1531.09      40 1514.63      45 1511.87      60 1507.58
      85 1484.02     150 1437.72     180  1410.2     185    1408   214.9 1403.45
   289.9 1401.94   324.9 1398.24   336.8 1398.24   351.8 1398.24   369.9  1398.8
   379.9 1406.94   394.9  1410.9   404.9 1411.81   419.9 1408.73   429.9 1409.08
   484.7 1429.77   489.7 1431.15   504.7 1430.81   519.7  1434.7   544.6 1456.18
   554.6 1463.37   594.5 1488.85   609.5 1497.16   624.4 1507.61   689.3 1546.49
#Mann= 3 , 0 , 0
       0      .1       0   336.8    .045       0   351.8      .1       0
Bank Sta=336.8,351.8
XS Rating Curve= 0 ,0
Exp/Cntr=0.3,0.1

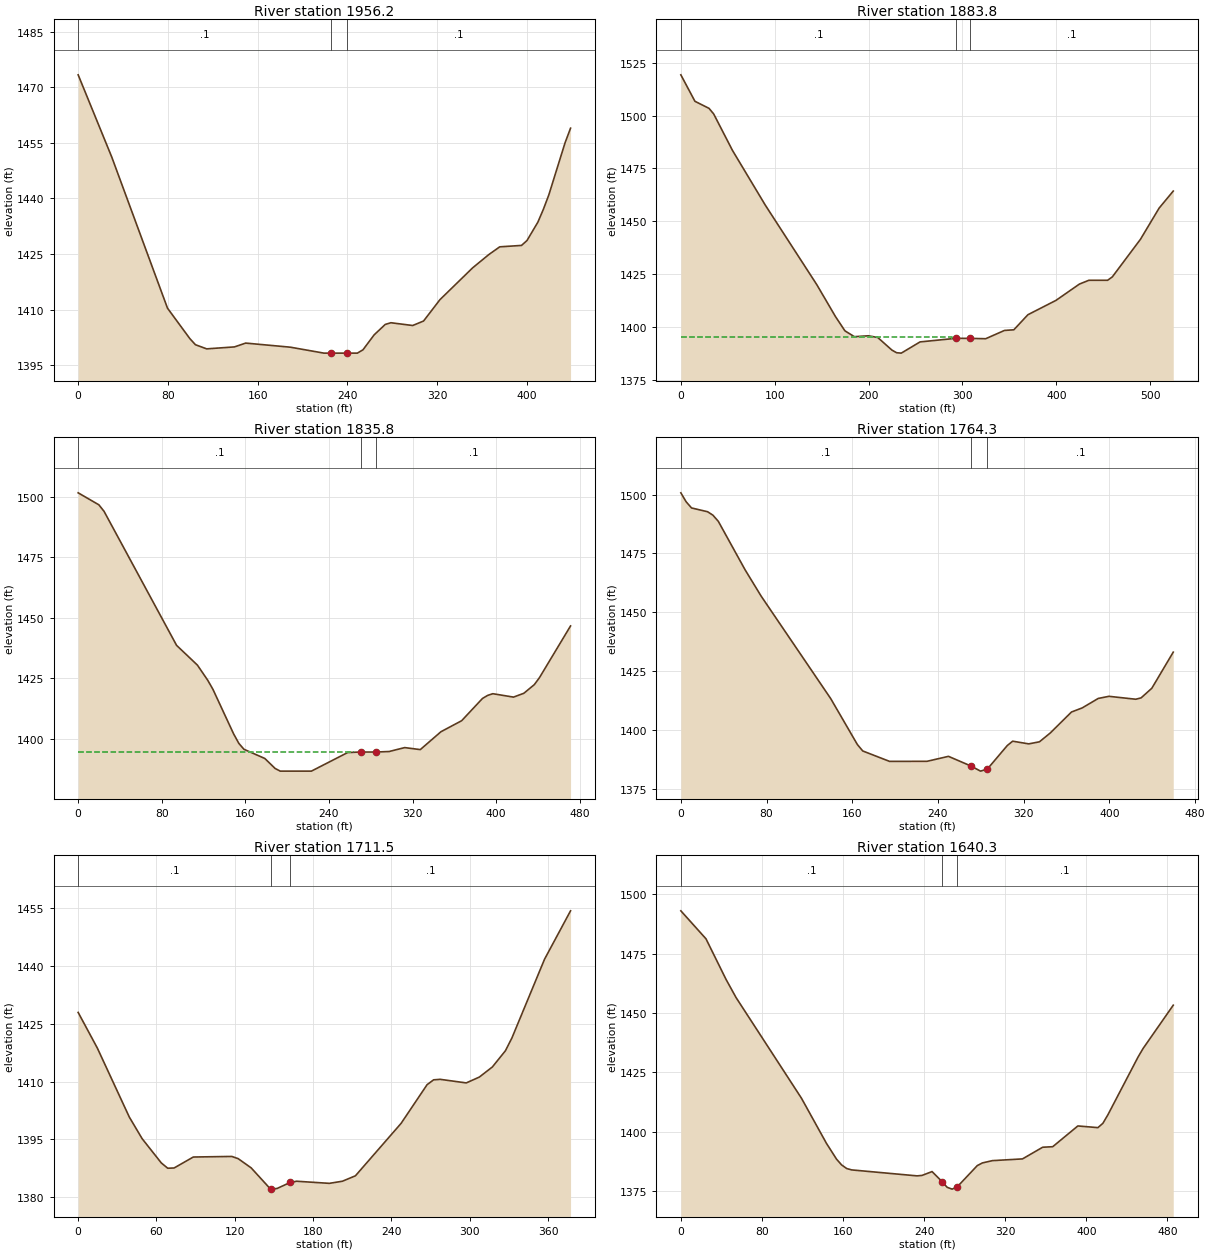
Type RM Length L Ch R = 1 ,1956.2  ,71.2,72.4,72.7
XS GIS Cut Line= 3
     1759532.114      244368.269     1759537.274      244646.905
     1759530.394      244806.862
#Sta/Elev= 30
       0 1473.33    29.9 1451.18    79.6 1410.38    99.5 1402.17   104.5 1400.51
   114.5 1399.39   139.3 1399.92   149.3 1400.95   189.1 1399.84     219 1398.24
     225 1398.24     240 1398.24   248.8 1398.24   253.8 1399.13   263.8 1403.18
   273.7 1405.99   278.7 1406.44   298.1 1405.69   307.8  1406.9   322.4 1412.66
   351.5 1421.24     366 1424.84   375.7 1426.92   395.1  1427.3     400 1428.63
   409.7 1433.59   414.5 1436.98   419.4  1440.9   433.9 1454.99   438.8 1458.93
#Mann= 3 , 0 , 0
       0      .1       0     225    .045       0     240      .1       0
#XS Ineff= 2 , 0
          150.13 1400.84
Permanent Ineff=
       F       F
Bank Sta=225,240
XS Rating Curve= 0 ,0
Exp/Cntr=0.3,0.1

Type RM Length L Ch R = 1 ,1883.8  ,47.7,48,49.1
XS GIS Cut Line= 2
     1759473.046      244297.345     1759458.875      244821.681
#Sta/Elev= 30
       0 1519.31      15 1506.78      30 1503.44      35 1500.77      55 1483.51
    89.9 1457.64   144.9 1419.88   164.8 1404.76   174.8 1398.07   184.8 1395.31
   199.8 1395.73   209.8 1394.91   224.8 1388.97   229.8 1387.71   234.8 1387.52
   254.8 1392.83   292.9 1394.53   307.9 1394.51   324.7 1394.34   344.7 1398.26
   354.7 1398.57   369.7 1405.71   399.6  1412.5   424.6 1420.23   434.6 1422.01
   454.6 1422.01   459.6 1423.62   489.6 1441.44   509.5 1456.22   524.5 1464.26
#Mann= 3 , 0 , 0
       0      .1       0   292.9    .045       0   307.9      .1       0
#XS Ineff= 2 , 0
          288.57 1395.15
Permanent Ineff=
       F       F
Bank Sta=292.9,307.9
XS Rating Curve= 0 ,0
Exp/Cntr=0.3,0.1

Type RM Length L Ch R = 1 ,1835.8  ,71.7,71.6,71.5
XS GIS Cut Line= 2
     1759428.431      244315.437     1759409.536      244786.237
#Sta/Elev= 30
       0 1501.71    19.8 1496.76    24.8 1494.04    94.2 1438.63   114.1 1430.48
     124 1424.21     129 1420.43   148.8    1402   153.8 1398.08   158.7 1395.65
   178.6 1391.87   188.5 1387.73   193.4 1386.63   223.2 1386.63   257.9 1394.31
   270.3 1394.53   285.3 1394.53   297.6 1394.74   312.5 1396.36   327.4 1395.53
   347.2 1402.93     367 1407.48   386.9 1416.67   391.8 1417.93   396.8 1418.64
   416.6 1417.24   426.5 1418.82   436.5 1422.39   441.4 1425.25   471.2 1446.67
#Mann= 3 , 0 , 0
       0      .1       0   270.3    .045       0   285.3      .1       0
#XS Ineff= 2 , 0
          264.39 1394.59
Permanent Ineff=
       F       F
Bank Sta=270.3,285.3
XS Rating Curve= 0 ,0
Exp/Cntr=0.3,0.1

Type RM Length L Ch R = 1 ,1764.3  ,52.3,52.7,53.2
XS GIS Cut Line= 2
     1759356.676      244306.349     1759339.477      244765.583
#Sta/Elev= 30
       0 1500.75       5  1496.9      10 1494.32      25 1492.71      30 1491.23
      35 1488.62    59.9  1468.1    74.9  1456.9   139.9 1413.32   164.8  1393.8
   169.8 1391.08   194.8 1386.66   229.8 1386.69   249.8  1388.8   271.1 1384.63
   279.7 1382.52   286.1 1383.41   304.7 1393.39   309.7 1395.24   324.7  1394.1
   334.7 1394.97   344.7 1398.68   364.6 1407.63   374.6 1409.37   389.6  1413.4
   399.6  1414.3   424.6 1413.06   429.6 1413.64   439.6 1417.72   459.6 1433.07
#Mann= 3 , 0 , 0
       0      .1       0   271.1    .045       0   286.1      .1       0
Bank Sta=271.1,286.1
XS Rating Curve= 0 ,0
Exp/Cntr=0.3,0.1

Type RM Length L Ch R = 1 ,1711.5  ,69.6,71.2,72.8
XS GIS Cut Line= 3
     1759303.357      244418.148     1759296.477      244545.426
     1759282.717      244794.823
#Sta/Elev= 30
       0 1427.99    14.7 1418.73    39.2  1400.8      49  1395.2    63.7 1388.89
    68.6 1387.52    73.5 1387.58    88.2 1390.43   117.7 1390.58   122.6    1390
   132.5 1387.62   147.4 1382.09   147.6  1382.1   152.4 1382.26   162.6 1383.85
   167.4 1384.14   192.4 1383.59   202.4 1384.14   212.4 1385.55   247.4 1399.18
   267.3 1409.22   272.3 1410.48   277.3 1410.61   297.3 1409.68   307.3 1411.19
   317.3 1413.82   327.3 1418.03   332.3 1421.37   357.3 1441.83   377.2 1454.38
#Mann= 3 , 0 , 0
       0      .1       0   147.6    .045       0   162.6      .1       0
Bank Sta=147.6,162.6
XS Rating Curve= 0 ,0
Exp/Cntr=0.3,0.1

Type RM Length L Ch R = 1 ,1640.3  ,50.8,50.1,49.3
XS GIS Cut Line= 2
     1759257.265      244308.367     1759195.856       244790.19
#Sta/Elev= 30
       0 1492.96    24.8 1481.18    44.6 1464.08    54.5 1456.43     119 1414.07
   143.7 1395.04   153.6 1388.43   158.6 1386.01   163.6  1384.5   168.5 1383.92
     233 1381.41   237.9  1381.6   247.8 1383.22   257.6 1379.01   262.7 1376.59
   267.6 1375.83   272.6 1376.78   292.4 1385.73   297.4 1386.85   307.3 1387.82
     337 1388.55   356.9 1393.46   366.8 1393.68   391.6 1402.42   411.4 1401.71
   416.3 1403.53   421.3 1407.16     451 1431.43     456 1435.05   485.7 1453.24
#Mann= 3 , 0 , 0
       0      .1       0   257.6    .045       0   272.6      .1       0
Bank Sta=257.6,272.6
XS Rating Curve= 0 ,0
Exp/Cntr=0.3,0.1

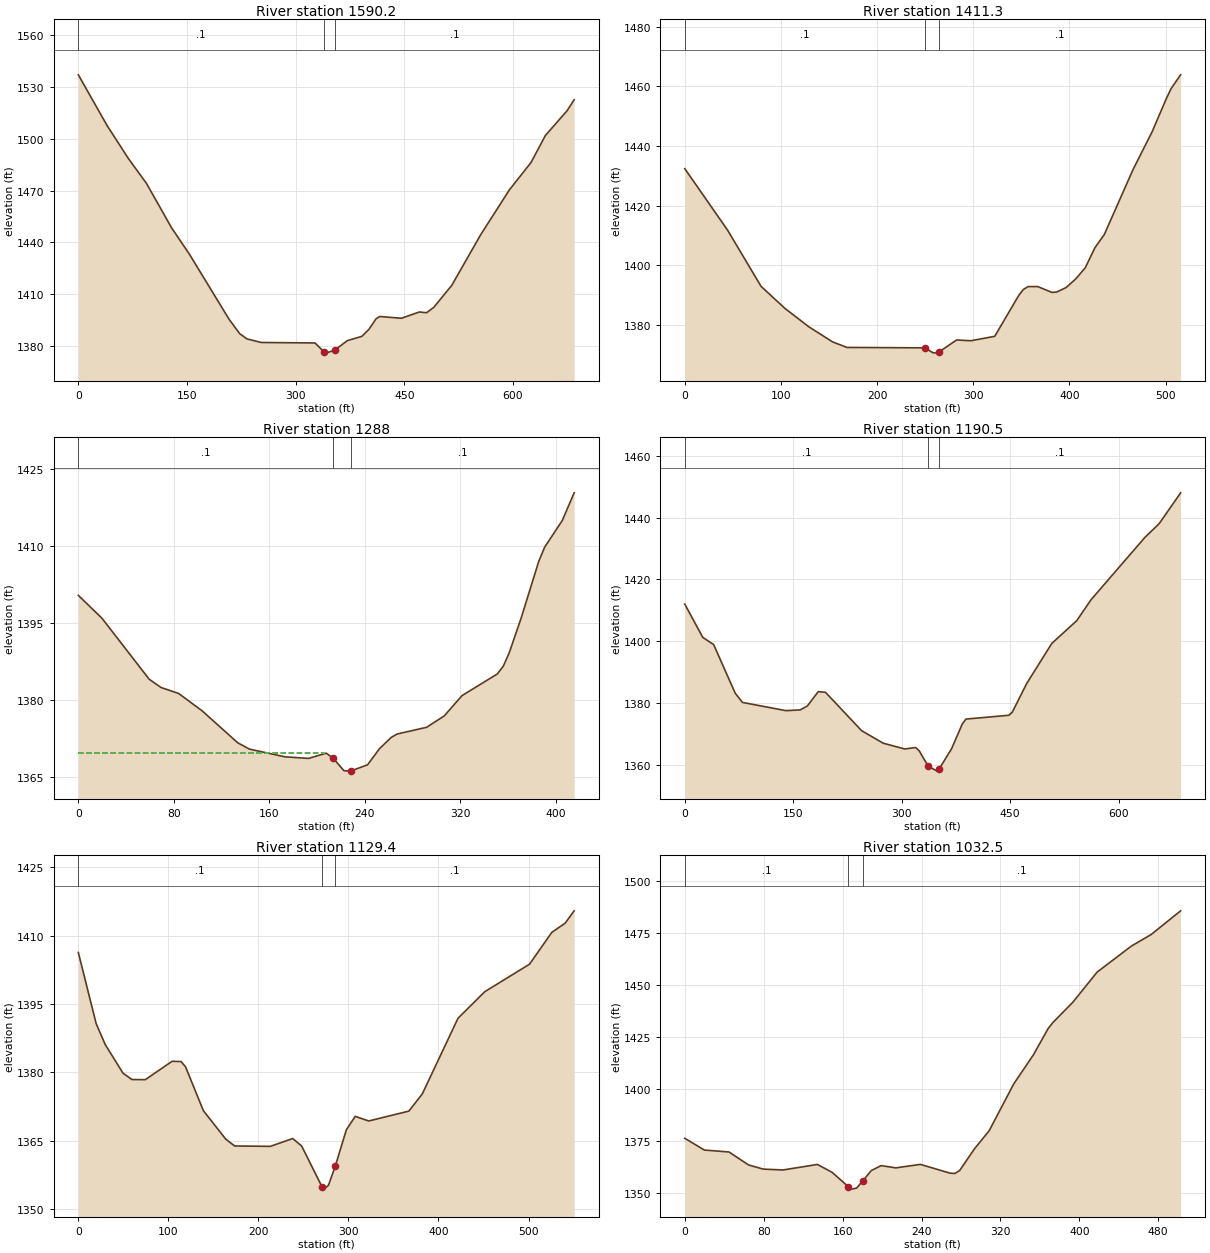
Type RM Length L Ch R = 1 ,1590.2  ,183.2,178.9,174.6
XS GIS Cut Line= 3
     1759206.236      244224.437     1759174.148      244564.551
     1759141.967      244905.955
#Sta/Elev= 30
       0 1537.11    39.6 1507.78    69.3 1488.46    94.1 1474.14   128.7 1448.43
   153.5    1433   207.9  1395.5   222.8 1386.99   232.7    1384   252.5 1381.91
   326.8 1381.62   338.8 1376.62   341.6 1375.73   353.8 1377.42   371.4 1382.98
   391.3 1385.43   401.3 1389.58   411.2 1395.72   416.2 1396.97     446 1395.94
   470.8 1399.59   480.8 1399.15   490.7 1402.28   515.6 1415.07   555.3 1444.28
   595.1  1470.4   624.9 1486.23   644.8 1501.94   674.6 1516.22   684.5 1522.65
#Mann= 3 , 0 , 0
       0      .1       0   338.8    .045       0   353.8      .1       0
Bank Sta=338.8,353.8
XS Rating Curve= 0 ,0
Exp/Cntr=0.3,0.1

Type RM Length L Ch R = 1 ,1411.3  ,126.2,123.3,120.3
XS GIS Cut Line= 2
      1758973.84      244292.621     1759022.652      244805.935
#Sta/Elev= 30
       0  1432.4    44.6 1411.76    79.3 1392.99   104.1 1385.61   128.9 1379.46
   153.7 1374.38   168.6 1372.53   249.8 1372.39   257.8 1370.78   262.8 1370.62
   264.8  1371.1   282.6 1375.02   297.5 1374.77   322.3 1376.25   347.1 1389.86
     352 1391.93     357  1392.9   366.9 1392.92   381.8 1390.96   386.7 1391.09
   396.6  1392.6   406.6  1395.5   416.5 1399.24   426.4 1405.88   436.3 1410.38
     466 1432.03   485.9 1444.72   500.8 1455.93   505.7 1459.23   515.6 1463.84
#Mann= 3 , 0 , 0
       0      .1       0   249.8    .045       0   264.8      .1       0
Bank Sta=249.8,264.8
XS Rating Curve= 0 ,0
Exp/Cntr=0.3,0.1

Type RM Length L Ch R = 1 ,1288    ,95,97.6,96.4
XS GIS Cut Line= 2
     1758825.829      244335.135      1758918.73      244739.803
#Sta/Elev= 30
       0 1400.41    19.8 1395.95    59.3 1384.07    69.2 1382.46      84 1381.29
   103.8 1377.88   133.5 1371.67   143.3 1370.44     173 1368.94   192.8 1368.63
   207.6 1369.65   213.5 1368.64   222.4 1366.24   227.4 1366.15   228.5 1366.21
   242.2 1367.38   252.1  1370.5     262 1372.72   266.9 1373.38   291.6 1374.69
   306.4 1376.91   321.3 1380.87   350.9  1385.1   355.9 1386.63   360.8  1389.2
   370.7  1395.9   385.5    1407   390.5  1409.8   405.3 1415.02   415.2  1420.4
#Mann= 3 , 0 , 0
       0      .1       0   213.5    .045       0   228.5      .1       0
#XS Ineff= 2 , 0
          205.49  1369.6
Permanent Ineff=
       F       F
Bank Sta=213.5,228.5
XS Rating Curve= 0 ,0
Exp/Cntr=0.3,0.1

Type RM Length L Ch R = 1 ,1190.5  ,69.2,61,58.8
XS GIS Cut Line= 3
     1758739.786      244225.027     1758779.444      244566.974
     1758872.251      244895.678
#Sta/Elev= 30
       0 1412.04    24.9 1401.29    39.9 1398.98    69.8 1383.24    79.8 1380.29
   139.7 1377.64   159.6 1377.87   169.6 1379.16   184.6 1383.78   194.6 1383.56
   244.5 1371.18   274.4 1367.12   304.3 1365.25   319.3 1365.73   324.3 1364.63
   336.7 1359.66   349.2  1358.1   351.7 1358.76     369 1365.33   383.8 1373.32
   388.8 1374.91   448.2 1376.14   453.1 1377.19   472.9  1386.4   507.6 1399.34
   542.2 1406.72     562 1413.49   636.3 1433.57   656.1 1438.02   685.8 1447.99
#Mann= 3 , 0 , 0
       0      .1       0   336.7    .045       0   351.7      .1       0
Bank Sta=336.7,351.7
XS Rating Curve= 0 ,0
Exp/Cntr=0.3,0.1

Type RM Length L Ch R = 1 ,1129.4  ,88.9,96.9,102.7
XS GIS Cut Line= 2
     1758621.133      244314.665     1758816.382      244829.554
#Sta/Elev= 30
       0 1406.32    19.8  1390.7    29.8 1386.12    49.6 1379.81    59.5 1378.41
    74.4 1378.38   104.2 1382.42   114.1 1382.35   119.1  1381.2   138.9 1371.56
   163.7 1365.32   173.6 1363.81   213.3 1363.73   238.1 1365.44     248 1363.82
   270.6 1354.86   272.8 1354.33   277.8 1355.16   285.6 1359.51   297.7 1367.38
   307.6 1370.32   322.5  1369.3   367.1 1371.47     382 1375.23   421.7 1391.87
   451.4  1397.7   501.1 1403.74   525.9 1410.74   540.7 1412.76   550.7 1415.47
#Mann= 3 , 0 , 0
       0      .1       0   270.6    .045       0   285.6      .1       0
Bank Sta=270.6,285.6
XS Rating Curve= 0 ,0
Exp/Cntr=0.3,0.1

Type RM Length L Ch R = 1 ,1032.5  ,115.3,116.8,118.3
XS GIS Cut Line= 2
     1758603.813      244394.969     1758663.647      244894.112
#Sta/Elev= 30
       0 1376.18    19.9 1370.54    44.8 1369.62    64.7 1363.38    79.6 1361.39
    99.6 1360.98   134.4 1363.64   149.3 1359.87   165.7 1353.01   169.2 1351.78
   174.2 1352.28   180.7 1355.88   189.1 1360.71   199.1 1363.07     214 1361.99
   238.9 1363.67   268.8 1359.47   273.8 1359.29   278.7 1360.72   293.7 1371.15
   308.6 1379.82   333.5 1402.31   353.4 1416.24   368.3 1428.84   373.3 1431.84
   393.2 1441.43   418.1 1456.03   452.9 1468.55   472.8 1474.05   502.7 1485.44
#Mann= 3 , 0 , 0
       0      .1       0   165.7    .045       0   180.7      .1       0
Bank Sta=165.7,180.7
XS Rating Curve= 0 ,0
Exp/Cntr=0.3,0.1

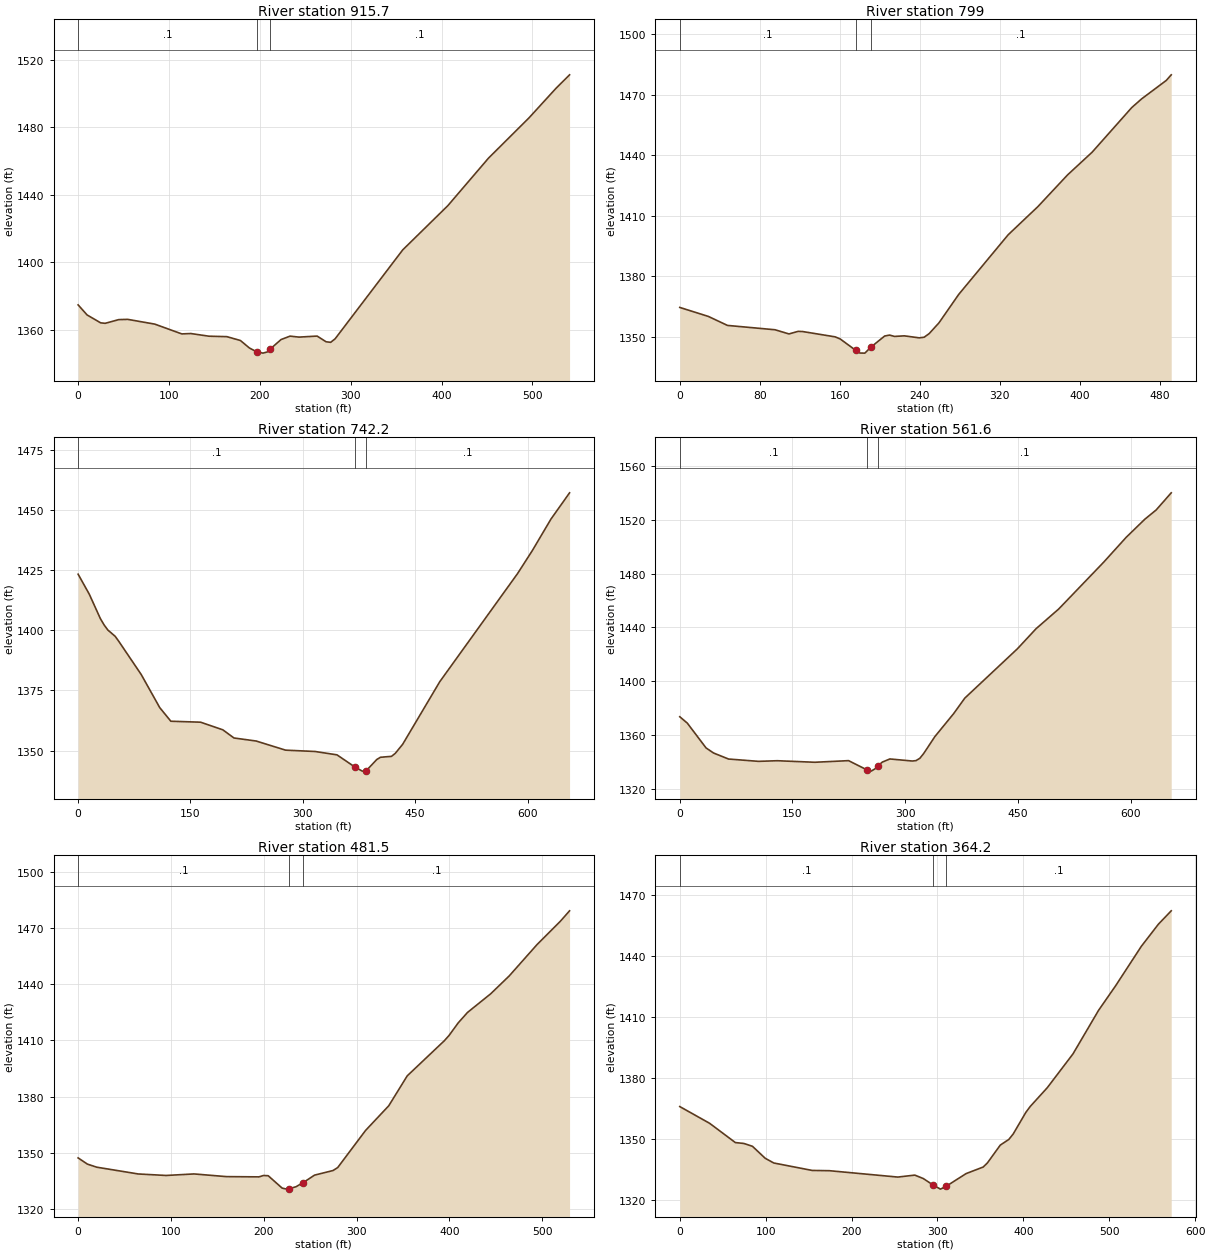
Type RM Length L Ch R = 1 ,915.7   ,117.3,116.8,116.2
XS GIS Cut Line= 2
      1758499.89      244355.604     1758528.233      244895.687
#Sta/Elev= 30
       0 1374.86     9.9 1368.89    24.8 1364.22    29.8 1363.94    44.7 1366.13
    54.6 1366.28    84.4 1363.46   114.1 1357.66     124 1357.89   143.9 1356.31
   163.7 1356.04   178.6 1353.76   188.5 1349.32   196.4  1347.1   203.4 1346.28
   208.4 1347.03   211.4  1348.7   223.3 1354.32   233.2 1356.34   243.1 1355.77
     263 1356.38   272.9    1353   277.9 1352.68   282.8 1354.75   357.2 1407.43
   406.9 1433.66   451.5 1461.73   496.2 1485.66   525.9 1503.17   540.8 1511.14
#Mann= 3 , 0 , 0
       0      .1       0   196.4    .045       0   211.4      .1       0
Bank Sta=196.4,211.4
XS Rating Curve= 0 ,0
Exp/Cntr=0.3,0.1

Type RM Length L Ch R = 1 ,799     ,50.2,56.8,63.3
XS GIS Cut Line= 4
      1758482.57      244424.886     1758441.631      244516.212
     1758392.819      244528.809     1758418.012      244868.919
#Sta/Elev= 30
       0 1364.49    28.6 1360.02    47.7 1355.56    95.3  1353.4   109.2 1351.33
   118.4 1352.61     123 1352.51   155.4 1349.88   160.4 1348.85   175.8 1343.25
   180.2 1341.85   185.1  1341.8   190.8 1344.63   204.9 1350.29   209.8 1350.76
   214.8 1350.09   224.6 1350.38   239.5 1349.38   244.4  1349.7   249.4 1351.48
   259.2 1356.82     279 1370.97   328.4 1400.54   358.1 1414.51   387.7 1430.22
   412.4 1441.56     452  1463.7   461.9 1468.03   486.6 1477.21   491.5 1479.97
#Mann= 3 , 0 , 0
       0      .1       0   175.8    .045       0   190.8      .1       0
Bank Sta=175.8,190.8
XS Rating Curve= 0 ,0
Exp/Cntr=0.3,0.1

Type RM Length L Ch R = 1 ,742.2   ,186.6,180.5,174.6
XS GIS Cut Line= 5
     1758496.044      244264.801     1758449.504      244487.869
     1758347.156       244522.51     1758332.984      244588.643
     1758366.051      244839.002
#Sta/Elev= 30
       0 1423.34    14.9 1415.04    29.7 1404.88    34.7 1402.25    39.6 1400.15
    49.5  1397.5    54.5 1395.33    84.2 1381.64     109 1367.84   123.8 1362.19
   163.5 1361.79   193.2 1358.62   208.1 1355.22   237.7 1353.96     277 1350.16
   316.3 1349.61   345.6 1348.21   369.5 1343.15   379.4 1341.44   384.5 1341.57
   398.7 1346.26   403.6  1347.2   418.4 1347.59   423.4 1348.82   433.3 1352.61
   482.8 1378.62   586.8 1423.66   606.6 1433.27   631.3 1446.28   656.1 1457.18
#Mann= 3 , 0 , 0
       0      .1       0   369.5    .045       0   384.5      .1       0
Bank Sta=369.5,384.5
XS Rating Curve= 0 ,0
Exp/Cntr=0.3,0.1

Type RM Length L Ch R = 1 ,561.6   ,80.9,80.1,79.3
XS GIS Cut Line= 2
     1758147.184      244302.069     1758178.675      244955.521
#Sta/Elev= 30
       0 1373.65      10 1368.95      35 1350.48      45 1346.73    64.9 1342.25
   104.9 1340.52   129.8 1340.99   179.8 1339.84   224.7 1341.05     249 1334.24
   254.7 1333.26   259.7 1334.87     264 1337.32   269.7    1340   279.7  1342.3
   309.6 1340.76   314.6 1341.09   319.6 1342.82   324.6 1346.27   339.6 1358.93
   364.6    1376   379.5 1387.54   449.5 1424.18   474.4 1439.12   504.4 1453.69
   564.3 1488.49   594.3 1506.98   619.2 1520.47   634.2  1527.3   654.2 1540.01
#Mann= 3 , 0 , 0
       0      .1       0     249    .045       0     264      .1       0
Bank Sta=249,264
XS Rating Curve= 0 ,0
Exp/Cntr=0.3,0.1

Type RM Length L Ch R = 1 ,481.5   ,120,117.4,114.4
XS GIS Cut Line= 2
     1758060.581      244331.986     1758106.244      244859.471
#Sta/Elev= 30
       0 1347.26      10 1343.95      20 1342.31    64.9 1338.68    94.9 1337.89
   124.9  1338.7   159.8 1337.27   194.8 1337.14   199.8 1337.88   204.8 1337.75
   219.8 1331.15   224.8  1330.6   227.3 1330.84   234.8 1331.88   242.3 1334.02
   254.7 1338.06   274.7 1340.53   279.7 1342.11   309.7  1361.9   334.7 1375.07
   354.6 1391.03   394.6 1409.78   399.6 1412.54   409.6 1419.34   419.6 1424.88
   444.6 1434.84   464.5 1444.35   494.5 1461.09   519.5 1473.47   529.5 1479.07
#Mann= 3 , 0 , 0
       0      .1       0   227.3    .045       0   242.3      .1       0
Bank Sta=227.3,242.3
XS Rating Curve= 0 ,0
Exp/Cntr=0.3,0.1

Type RM Length L Ch R = 1 ,364.2   ,123.4,119.9,116.8
XS GIS Cut Line= 2
     1757903.123      244265.853     1758018.068      244826.405
#Sta/Elev= 30
       0 1365.87    34.8 1357.63    64.7 1348.17    74.6 1347.73    84.6 1346.34
    99.5 1340.43   109.5 1338.12   154.2 1334.46   174.2 1334.33   253.8  1331.2
   273.7 1332.16   283.6 1330.46   295.1 1327.24   303.5 1325.27   310.1 1326.65
   333.4 1332.91   353.3 1336.14   358.3 1338.22   373.2 1346.93   383.1  1349.7
   388.1 1352.32     403 1363.05     408  1365.9   427.9 1375.15   457.8 1391.76
   487.6 1413.18   507.5  1425.3   537.4 1444.68   557.3 1455.57   572.2 1462.13
#Mann= 3 , 0 , 0
       0      .1       0   295.1    .045       0   310.1      .1       0
Bank Sta=295.1,310.1
XS Rating Curve= 0 ,0
Exp/Cntr=0.3,0.1

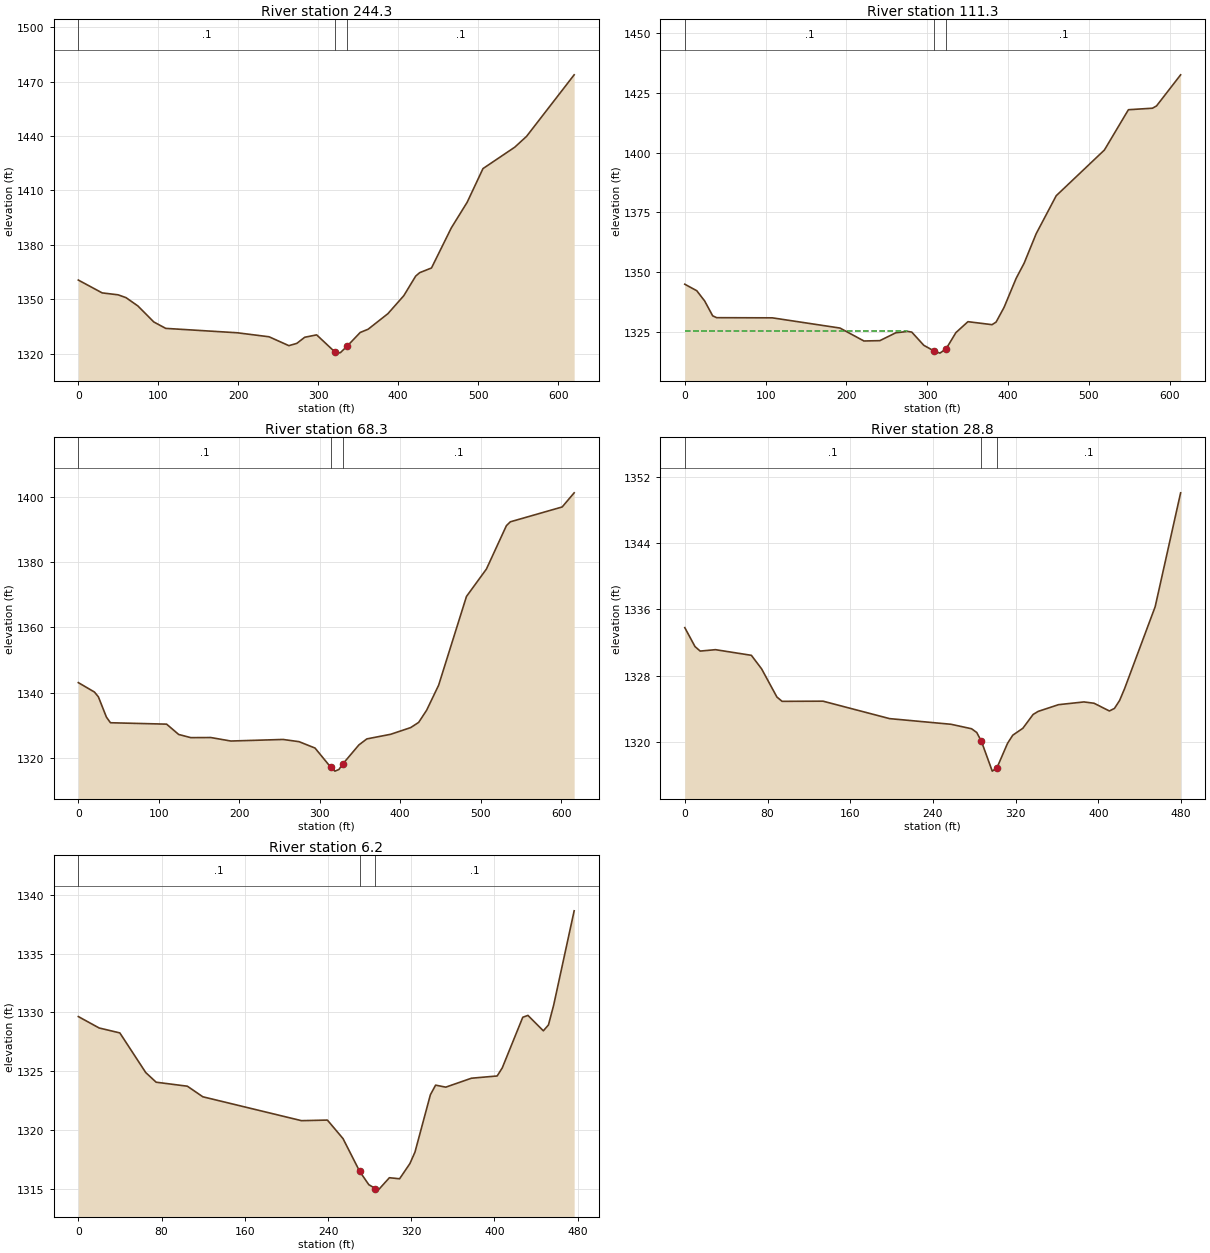
Type RM Length L Ch R = 1 ,244.3   ,133.8,133,132.1
XS GIS Cut Line= 3
     1757818.096      244267.428     1757825.968       244525.66
     1757948.786       244865.77
#Sta/Elev= 30
       0 1360.61    29.8 1353.54    49.7 1352.48    59.6 1350.93    74.5 1346.33
    94.4 1337.51   109.3 1333.98   198.7 1331.56   238.5 1329.35   263.3 1324.45
   273.2 1325.72   283.1 1329.08     298 1330.41   321.5 1320.71   322.8 1320.34
   327.7 1320.61   336.5 1324.35   352.5 1331.74   362.4 1333.52   387.1 1342.08
     407 1352.01   421.8 1362.78   426.8 1364.68   441.6 1367.27   466.4 1389.37
   486.2 1403.48     506 1422.05   545.7 1433.84   560.5 1439.82     620 1473.73
#Mann= 3 , 0 , 0
       0      .1       0   321.5    .045       0   336.5      .1       0
Bank Sta=321.5,336.5
XS Rating Curve= 0 ,0
Exp/Cntr=0.3,0.1

Type RM Length L Ch R = 1 ,111.3   ,44.6,43,41.2
XS GIS Cut Line= 3
     1757720.471      244300.494     1757698.427      244555.577
     1757833.841      244886.239
#Sta/Elev= 30
       0 1344.86    14.8 1342.14    24.6 1337.83    34.5 1331.61    39.4 1330.84
   108.3 1330.77     192 1326.49   221.6 1321.07   241.3 1321.21     261  1324.5
   275.9 1325.07   280.8 1324.79   295.7 1319.25   308.3  1316.9   315.6 1315.98
   323.3 1317.79   335.4 1324.58   350.3 1329.16   380.1 1327.91   385.1 1328.99
     395 1335.18   409.9 1347.31   419.8 1353.68   434.7 1366.03   459.5 1381.96
   519.1 1401.11   548.8    1418   578.6 1418.64   583.6  1419.6   613.4 1432.63
#Mann= 3 , 0 , 0
       0      .1       0   308.3    .045       0   323.3      .1       0
#XS Ineff= 2 , 0
          274.67 1325.12
Permanent Ineff=
       F       F
Bank Sta=308.3,323.3
XS Rating Curve= 0 ,0
Exp/Cntr=0.3,0.1

Type RM Length L Ch R = 1 ,68.3    ,30,39.5,45
XS GIS Cut Line= 3
       1757706.3       244295.77     1757657.488      244555.577
     1757789.753      244881.515
#Sta/Elev= 30
       0 1343.08      20  1340.2    24.9 1338.74    34.9 1332.52    39.9 1330.79
   109.7 1330.36   124.7  1327.2   139.7 1326.23   164.6 1326.26   189.5 1325.19
   254.4 1325.67   274.3 1324.99   294.1 1323.04   313.5 1317.21   318.8 1315.97
   323.8 1316.47   328.5 1318.13   348.6 1323.99   358.5 1325.84   388.2 1327.26
     413 1329.31   422.9  1330.9   432.8 1334.63   447.7 1342.29   482.3 1369.48
   507.1 1377.88   531.9 1391.16   536.8 1392.34   601.2 1396.89   616.1 1401.22
#Mann= 3 , 0 , 0
       0      .1       0   313.5    .045       0   328.5      .1       0
Bank Sta=313.5,328.5
XS Rating Curve= 0 ,0
Exp/Cntr=0.3,0.1

Type RM Length L Ch R = 1 ,28.8    ,24.5,22.6,19.2
XS GIS Cut Line= 4
     1757658.413      244314.161     1757638.173      244575.833
     1757640.341       244620.65     1757716.241       244775.34
#Sta/Elev= 30
       0 1333.81     9.9 1331.53    14.9 1330.99    29.7 1331.16    64.4 1330.48
    74.3 1328.85    89.1 1325.46    94.1 1324.94   133.7 1324.96   198.1 1322.86
   257.5 1322.18   277.4 1321.64   282.4 1321.19   286.9 1320.13   297.4 1316.54
   301.9 1316.93   312.2 1319.89   317.2 1320.86     327  1321.7   336.9 1323.36
   341.8 1323.73   361.5 1324.54   386.1 1324.87   395.9 1324.71   410.7 1323.78
   415.6 1324.09   420.6 1325.05   425.5  1326.5     455 1336.34   479.6 1350.04
#Mann= 3 , 0 , 0
       0      .1       0   286.9    .045       0   301.9      .1       0
Bank Sta=286.9,301.9
XS Rating Curve= 0 ,0
Exp/Cntr=0.3,0.1

Type RM Length L Ch R = 1 ,6.2     ,3.8,6.2,14.2
XS GIS Cut Line= 4
     1757630.221      244332.232     1757613.596      244596.073
     1757620.101      244619.927     1757702.506      244788.352
#Sta/Elev= 30
       0 1329.65      20 1328.68    39.9 1328.26    64.8 1324.89    74.8 1324.07
   104.8 1323.73   119.7 1322.83   214.5  1320.8   239.4 1320.85   254.4 1319.28
   270.5 1316.48   279.2 1315.36   285.5 1315.03   289.1 1314.98     299 1315.95
   308.8 1315.86   318.7 1317.15   323.6 1318.13   338.4    1323   343.4 1323.82
   353.2 1323.65   377.9 1324.41   402.6  1324.6   407.5 1325.29   427.2 1329.59
   432.2 1329.75     447 1328.44   451.9 1328.94   456.9 1330.62   476.6 1338.64
#Mann= 3 , 0 , 0
       0      .1       0   270.5    .045       0   285.5      .1       0
Bank Sta=270.5,285.5
XS Rating Curve= 0 ,0
Exp/Cntr=0.3,0.1

Chan Stop Cuts=-1
Use User Specified Reach Order=0